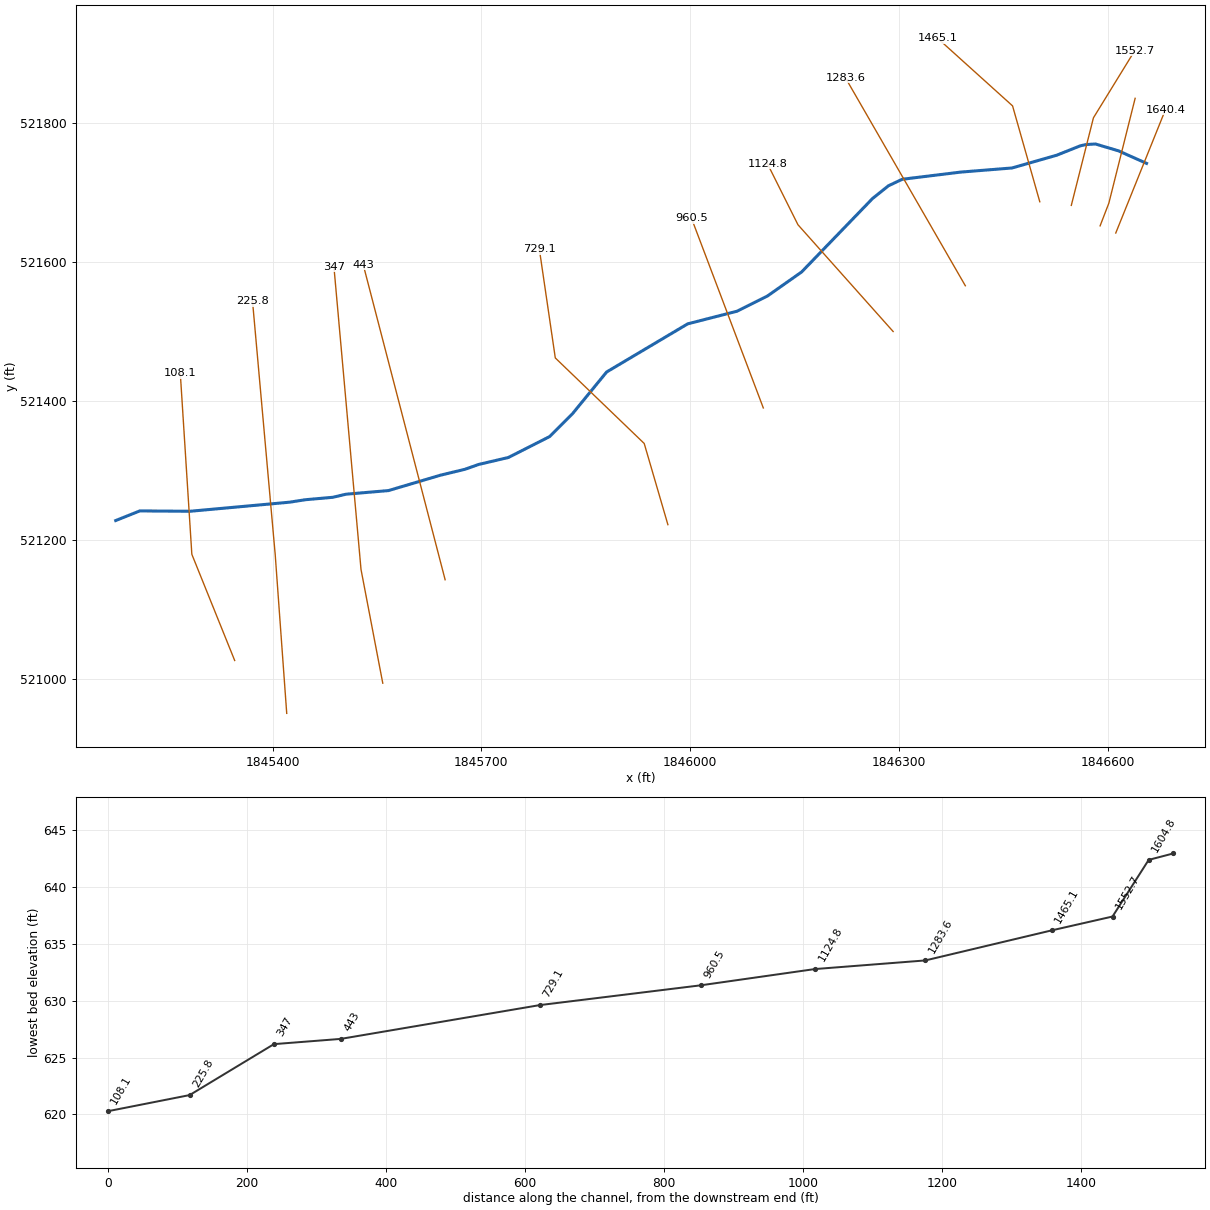
--- UPTHRMILFK.prj (project) ---

Proj Title=UPTHRMILFK
Current Plan=p01
Default Exp/Contr=0,0
English Units
Geom File=g01
Flow File=f01
Plan File=p01
BEGIN DESCRIPTION:
END DESCRIPTION:
DSS Export Rating Curves= 0
DSS Export Rating Curve Sorted= 0
DSS Export Volume Flow Curves= 0
DXF OffsetX= 0
DXF OffsetY= 0
DXF ScaleX= 0
DXF ScaleY= 0

--- UPTHRMILFK.p01 (plan) ---

Plan Title=Floodplain
Program Version=4.00
Geom File=g01
Flow File=f01
K Sum by GR=0
Std Step Tol=0.01
Critical Tol=0.01
Num of Std Step Trials=20
Max Error Tol=0.3
Flow Tol Ratio=0.001
Split Flow NTrial=30
Split Flow Tol=0.02
Split Flow Ratio=0.02
Log Output Level=0
Friction Slope Method=1
Unsteady Friction Slope Method=2
Unsteady Bridges Friction Slope Method=1
Global Log Level=0
CheckData=False
Run HTab=0
Run UNet=0
Run PostProcess=0
UNET Theta=0
UNET Theta Warmup=0
UNET ZTol=0
UNET ZSATol=0
UNET MxIter=0
UNET MaxInSteps=0
UNET DtIC=0
UNET DtMin=0
UNET MaxCRTS=0
UNET WFStab=0
UNET SFStab=0
UNET WFX=0
UNET SFX=0
UNET DSS MLevel=0
UNET DZMax Abort=0
UNET Convert EG Bridges=0
UNET Use Existing IB Tables=0
UNET Froude Limit=0
UNET Froude Power=0
Write IC File=0
Echo Input=False
Echo Output=False
Write Detailed=0

--- UPTHRMILFK.f01 (steady flow) ---

Flow Title=NFF Regression Equation
Program Version=4.10
Number of Profiles= 1
Profile Names=P100yr
River Rch & RM=UPTHRMILFK,Main            ,1640.4
688.7126
River Rch & RM=UPTHRMILFK,Main            ,1465.1
 690.007
River Rch & RM=UPTHRMILFK,Main            ,1124.8
1065.912
River Rch & RM=UPTHRMILFK,Main            ,729.1
 1068.77
Boundary for River Rch & Prof#=UPTHRMILFK,Main            , 1
Up Type= 0
Dn Type= 3
Dn Slope=0.022
DSS Import GetInterval= 0
DSS Import GetPeak= 0
DSS Import FillOption= 0

--- UPTHRMILFK.g01 (geometry) ---

Geom Title=USGS 10m DEM
Program Version=4.10

River Reach=UPTHRMILFK      ,Main
Reach XY= 30
     1846656.047      521741.489     1846615.755      521759.519
     1846582.609      521769.354     1846569.191      521768.564
     1846560.993      521766.771      1846526.88      521753.208
     1846462.675      521734.879      1846389.12      521728.989
     1846305.005      521718.659     1846285.185       521709.32
     1846262.286      521691.001     1846160.379      521585.455
     1846111.245      521550.879     1846067.571      521529.042
       1845996.6      521510.845     1845880.135      521441.693
     1845831.002      521381.641     1845798.246      521348.886
      1845738.88      521318.777     1845696.339      521308.851
     1845676.491      521301.846     1845641.272       521293.35
      1845566.54      521271.252     1845505.827      521266.071
      1845486.33      521261.566     1845447.208      521258.119
     1845424.465      521254.573     1845281.433       521241.52
     1845209.166       521242.03     1845174.626      521228.208

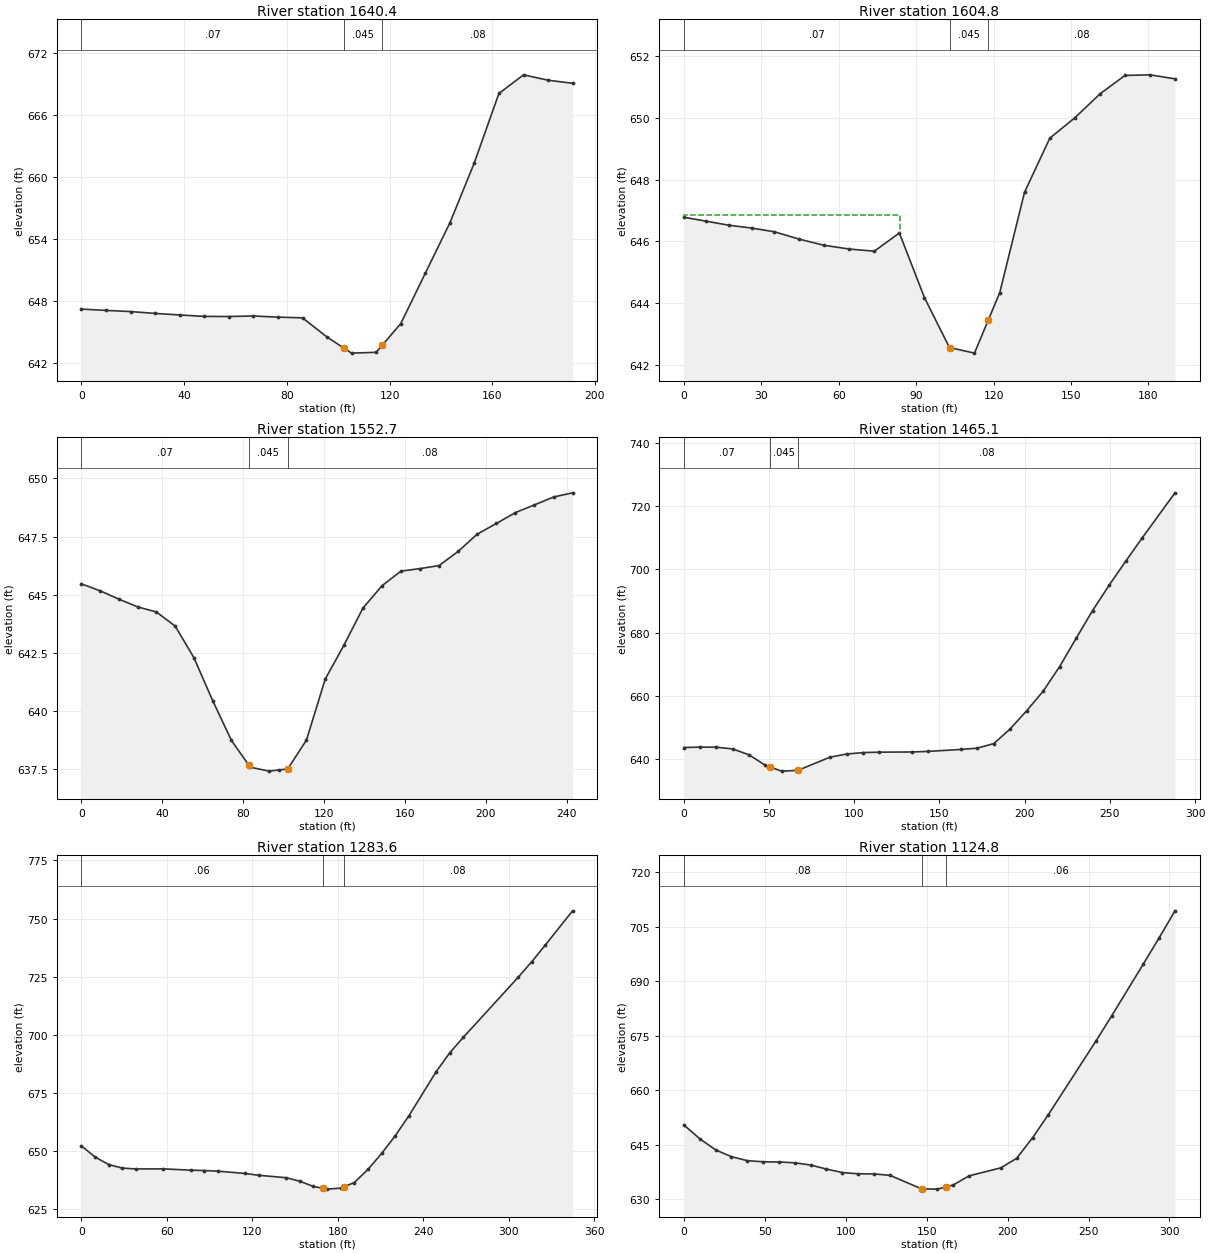
Type RM Length L Ch R = 1 ,1640.4  ,32.5,35.6,38.7
XS GIS Cut Line= 2
     1846611.819      521641.386     1846683.277      521818.838
#Sta/Elev= 23
       0  647.22     9.6  647.09    19.1  646.98    28.7   646.8    38.3  646.65
    47.8  646.51    57.4   646.5      67  646.55    76.5  646.44    86.1  646.37
    95.6  644.52   102.1  643.46   105.2  642.95   114.8  643.03   117.1   643.7
   124.4  645.82   133.9  650.68   143.5  655.57     153  661.38   162.6  668.12
   172.2  669.93   181.7  669.41   191.3  669.11
#Mann= 3 , 0 , 0
       0     .07       0   102.1    .045       0   117.1     .08       0
Bank Sta=102.1,117.1
XS Rating Curve= 0 ,0
Exp/Cntr=0.3,0.1

Type RM Length L Ch R = 1 ,1604.8  ,52.9,52,52
XS GIS Cut Line= 3
     1846589.321      521651.713     1846601.901      521684.342
     1846639.671      521835.013
#Sta/Elev= 23
       0  646.78     8.7  646.65    17.5  646.52    26.2  646.43      35  646.31
    44.7  646.07    54.4  645.87    64.1  645.75    73.8  645.68    83.5  646.27
    93.2  644.18   102.9  642.56     103  642.56   112.6  642.38     118  643.46
   122.4  644.34     132  647.59   141.8  649.34   151.5     650   161.2  650.77
   170.9  651.37   180.6  651.39   190.3  651.26
#Mann= 3 , 0 , 0
       0     .07       0     103    .045       0     118     .08       0
#XS Ineff= 2 , 0
           83.57  646.85
Permanent Ineff=
       F       F
Bank Sta=103,118
XS Rating Curve= 0 ,0
Exp/Cntr=0.3,0.1

Type RM Length L Ch R = 1 ,1552.7  ,74.7,87.6,99.3
XS GIS Cut Line= 3
     1846547.943      521681.138     1846579.764      521807.024
     1846639.022      521903.389
#Sta/Elev= 29
       0  645.46     9.3  645.16    18.6   644.8    27.8  644.47    37.1  644.25
    46.4  643.64    55.6  642.29    64.9  640.44    74.2  638.72    82.7  637.67
    83.5  637.57    92.8   637.4    97.7  637.45     102  637.49   111.3  638.73
   120.6  641.36   129.8  642.81   139.3  644.42   148.7  645.38   158.1  646.01
   167.6  646.12     177  646.25   186.4  646.86   195.8   647.6   205.3  648.06
   214.7  648.53   224.1  648.86   233.6   649.2     243  649.38
#Mann= 3 , 0 , 0
       0     .07       0    82.7    .045       0     102     .08       0
Bank Sta=82.7,102
XS Rating Curve= 0 ,0
Exp/Cntr=0.3,0.1

Type RM Length L Ch R = 1 ,1465.1  ,175.3,181.5,187.2
XS GIS Cut Line= 3
     1846502.626      521686.342     1846463.519      521824.122
     1846355.896      521921.201
#Sta/Elev= 28
       0  643.65     9.6  643.78    19.1  643.75    28.6  643.21    38.2  641.35
    47.7  638.06    50.4  637.53    57.3  636.18    66.8  636.41    85.9  640.62
    95.5  641.59     105  642.04   114.6  642.18   133.7  642.24   143.2  642.42
   162.6  643.04   172.2  643.45   181.9   644.9   191.5  649.56   201.2   655.3
   210.9  661.52   220.5  669.26   230.2  678.21   239.8  686.96   249.5  694.96
   259.2  702.53   268.8  709.86   288.2  724.24
#Mann= 3 , 0 , 0
       0     .07       0    50.4    .045       0    66.8     .08       0
Bank Sta=50.4,66.8
XS Rating Curve= 0 ,0
Exp/Cntr=0.3,0.1

Type RM Length L Ch R = 1 ,1283.6  ,154.8,158.9,163.3
XS GIS Cut Line= 2
     1846395.631      521565.631     1846223.351      521864.445
#Sta/Elev= 30
       0  652.12     9.6  647.34    19.2   644.1    28.7  642.59    38.3  642.23
    57.5  642.26    76.6   641.7    86.2  641.54    95.8  641.28     115  640.27
   124.6  639.49   143.7  638.46   153.3  636.95   162.9  634.68   169.4  633.91
   172.5  633.54     182  633.96   184.4  634.56   191.6  636.37   201.2  642.04
   210.8  648.89   220.4  656.55     230  665.14   249.1  684.09   258.7  692.26
   268.3  698.96   306.6  724.65   316.2  731.39   325.8  738.61   344.9  753.32
#Mann= 3 , 0 , 0
       0     .06       0   169.4    .045       0   184.4     .08       0
Bank Sta=169.4,184.4
XS Rating Curve= 0 ,0
Exp/Cntr=0.3,0.1

Type RM Length L Ch R = 1 ,1124.8  ,172.5,164.3,156
XS GIS Cut Line= 3
     1846291.871      521499.869     1846155.066      521653.342
     1846111.316      521740.842
#Sta/Elev= 28
       0  650.46     9.8  646.66    19.6  643.58    29.4  641.72    39.2  640.62
      49  640.31    58.7  640.26    68.5  640.03    78.3  639.42    88.1   638.3
    97.9  637.35   107.7     637   117.5  636.96   127.3  636.58   146.9  632.84
   156.6  632.78   161.9   633.4   166.4  633.93   176.2  636.44   195.8  638.64
   205.6  641.28   215.4  646.92   225.2  653.33   254.5  673.54   264.3  680.52
   283.9  694.83   293.6     702   303.4  709.44
#Mann= 3 , 0 , 0
       0     .08       0   146.9    .045       0   161.9     .06       0
Bank Sta=146.9,161.9
XS Rating Curve= 0 ,0
Exp/Cntr=0.3,0.1

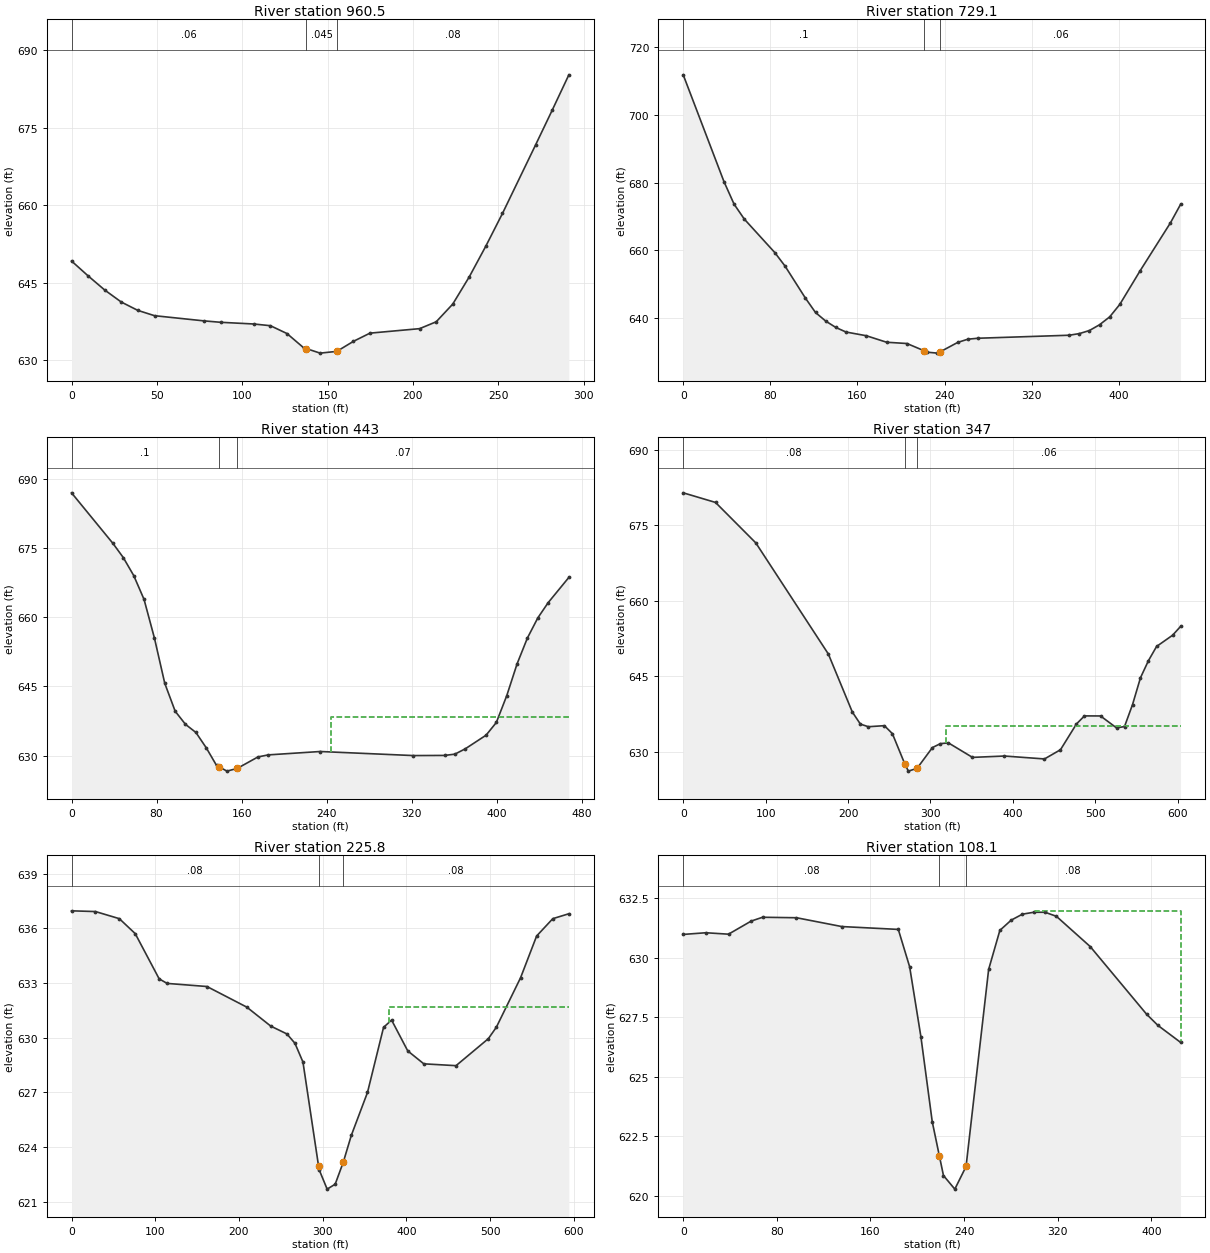
Type RM Length L Ch R = 1 ,960.5   ,221.3,231.4,241.5
XS GIS Cut Line= 2
     1846105.298      521390.028     1846002.154      521662.431
#Sta/Elev= 26
       0  649.19     9.7  646.31    19.4  643.58    29.1  641.25    38.8  639.63
    48.6   638.6    77.7  637.59    87.4  637.32   106.8  636.99   116.5  636.66
   126.2  635.14   135.9   632.4   137.4  632.24   145.6  631.35   155.4  631.69
   165.1  633.63   174.8  635.22   203.9  636.09   213.6  637.42   223.3  640.85
     233  646.14   242.7  652.09   252.4  658.39   271.9  671.73   281.6  678.43
   291.3  685.24
#Mann= 3 , 0 , 0
       0     .06       0   137.4    .045       0   155.4     .08       0
Bank Sta=137.4,155.4
XS Rating Curve= 0 ,0
Exp/Cntr=0.3,0.1

Type RM Length L Ch R = 1 ,729.1   ,298.4,286,273.4
XS GIS Cut Line= 4
      1845968.16      521222.291     1845934.132      521338.957
     1845806.354      521461.874     1845783.438      521618.124
#Sta/Elev= 30
       0  711.87    37.4  680.33    46.7  673.65    56.1  669.23    84.1  659.34
    93.5  655.35   112.2  645.89   121.5  641.62   130.9  639.08   140.2  637.19
   149.5  635.85   168.2  634.75   186.8  632.83   205.5  632.45   221.2  630.32
   224.2  629.88   233.5  629.61   236.2  630.03   252.2  632.79   261.5  633.73
   270.8  634.01   354.6   634.9   363.9  635.39   373.1  636.29   382.4     638
   391.7  640.32     401  644.01   419.6  653.92   447.5  668.11   456.8  673.57
#Mann= 3 , 0 , 0
       0      .1       0   221.2    .045       0   236.2     .06       0
Bank Sta=221.2,236.2
XS Rating Curve= 0 ,0
Exp/Cntr=0.3,0.1

Type RM Length L Ch R = 1 ,443     ,99.7,96,92.2
XS GIS Cut Line= 2
     1845648.021      521143.124     1845530.313      521595.902
#Sta/Elev= 30
       0  686.92      39  675.95    48.7  672.89    58.5     669    68.2  663.84
      78  655.44    87.7  645.66    97.5  639.61   107.2  636.77     117  635.01
   126.7   631.7   136.4  627.87   138.3  627.63   146.2  626.64   155.9  627.23
   175.4  629.72   185.2  630.16   233.9  630.89   321.6  630.01   350.9  630.04
   360.6  630.32   370.4  631.48   389.9  634.42   399.6  637.18   409.4     643
   419.1  649.88   428.8  655.47   438.6  659.83   448.3  663.12   467.8   668.6
#Mann= 3 , 0 , 0
       0      .1       0   138.3    .045       0   155.9     .07       0
#XS Ineff= 2 , 0
                          243.98          638.32
Permanent Ineff=
       F       F
Bank Sta=138.3,155.9
XS Rating Curve= 0 ,0
Exp/Cntr=0.3,0.1

Type RM Length L Ch R = 1 ,347     ,121,121.2,121
XS GIS Cut Line= 3
     1845558.394      520994.469     1845527.141       521157.91
     1845488.171      521593.255
#Sta/Elev= 30
       0  681.46    39.2  679.55    88.1  671.51   176.1  649.45   205.2  637.92
     215  635.52   224.7     635   244.1  635.21   253.8  633.63   268.8  627.64
   273.2  626.18   283.8  626.74   302.4  630.86   312.1  631.64   321.8  631.79
     351  628.91   389.8  629.18   438.4   628.6   457.8  630.43   477.2  635.55
   486.9  637.15   506.4  637.14   525.8  634.77   535.5  635.03   545.2  639.38
   554.9  644.74   564.6  648.14   574.4  650.94   593.8  653.17   603.5  654.91
#Mann= 3 , 0 , 0
       0     .08       0   268.8    .045       0   283.8     .06       0
#XS Ineff= 2 , 0
                          319.26          635.05
Permanent Ineff=
       F       F
Bank Sta=268.8,283.8
XS Rating Curve= 0 ,0
Exp/Cntr=0.3,0.1

Type RM Length L Ch R = 1 ,225.8   ,118.3,117.7,117.1
XS GIS Cut Line= 3
     1845420.373      520951.067     1845403.851      521178.869
     1845371.234      521543.246
#Sta/Elev= 30
       0  636.96    28.6  636.92    57.1  636.53    76.1  635.71   104.7  633.23
   114.2  632.98   161.8  632.81   209.4  631.68     238  630.64   257.3  630.21
   266.9   629.7   276.5  628.67   295.1  622.98   295.8  622.77   305.4   621.7
     315  621.97   324.7  623.18   334.3  624.65   353.6     627   372.8  630.57
   382.4  630.97   401.7  629.28   420.9  628.57   459.4  628.47     498  629.95
   507.6  630.58   536.5  633.29   555.7  635.58     575  636.53   594.2   636.8
#Mann= 3 , 0 , 0
       0     .08       0   295.1    .045       0   324.7     .08       0
#XS Ineff= 2 , 0
                          379.04           631.7
Permanent Ineff=
       F       F
Bank Sta=295.1,324.7
XS Rating Curve= 0 ,0
Exp/Cntr=0.3,0.1

Type RM Length L Ch R = 1 ,108.1   ,100.9,108.1,115.3
XS GIS Cut Line= 3
     1845345.575      521027.074     1845284.014      521179.677
     1845267.438      521439.549
#Sta/Elev= 26
       0  630.97    19.4  631.04    38.7  630.98    58.1  631.53    67.8  631.69
    96.8  631.67   135.5   631.3   183.8  631.18   193.5  629.61   203.1  626.68
   212.8  623.11     219  621.65   222.4  620.85   232.1  620.28   241.7  621.23
     261   629.5   270.6  631.14   280.3  631.57   289.9  631.82   299.6   631.9
   309.2   631.9   318.9  631.73   347.8  630.46     396  627.62   405.7  627.15
     425  626.44
#Mann= 3 , 0 , 0
       0     .08       0     219    .045       0   241.7     .08       0
#XS Ineff= 2 , 0
                          300.28          631.96
Permanent Ineff=
       F       F
Bank Sta=219,241.7
XS Rating Curve= 0 ,0
Exp/Cntr=0.3,0.1

Chan Stop Cuts=-1
Use User Specified Reach Order=0
Composite Channel Slope=5